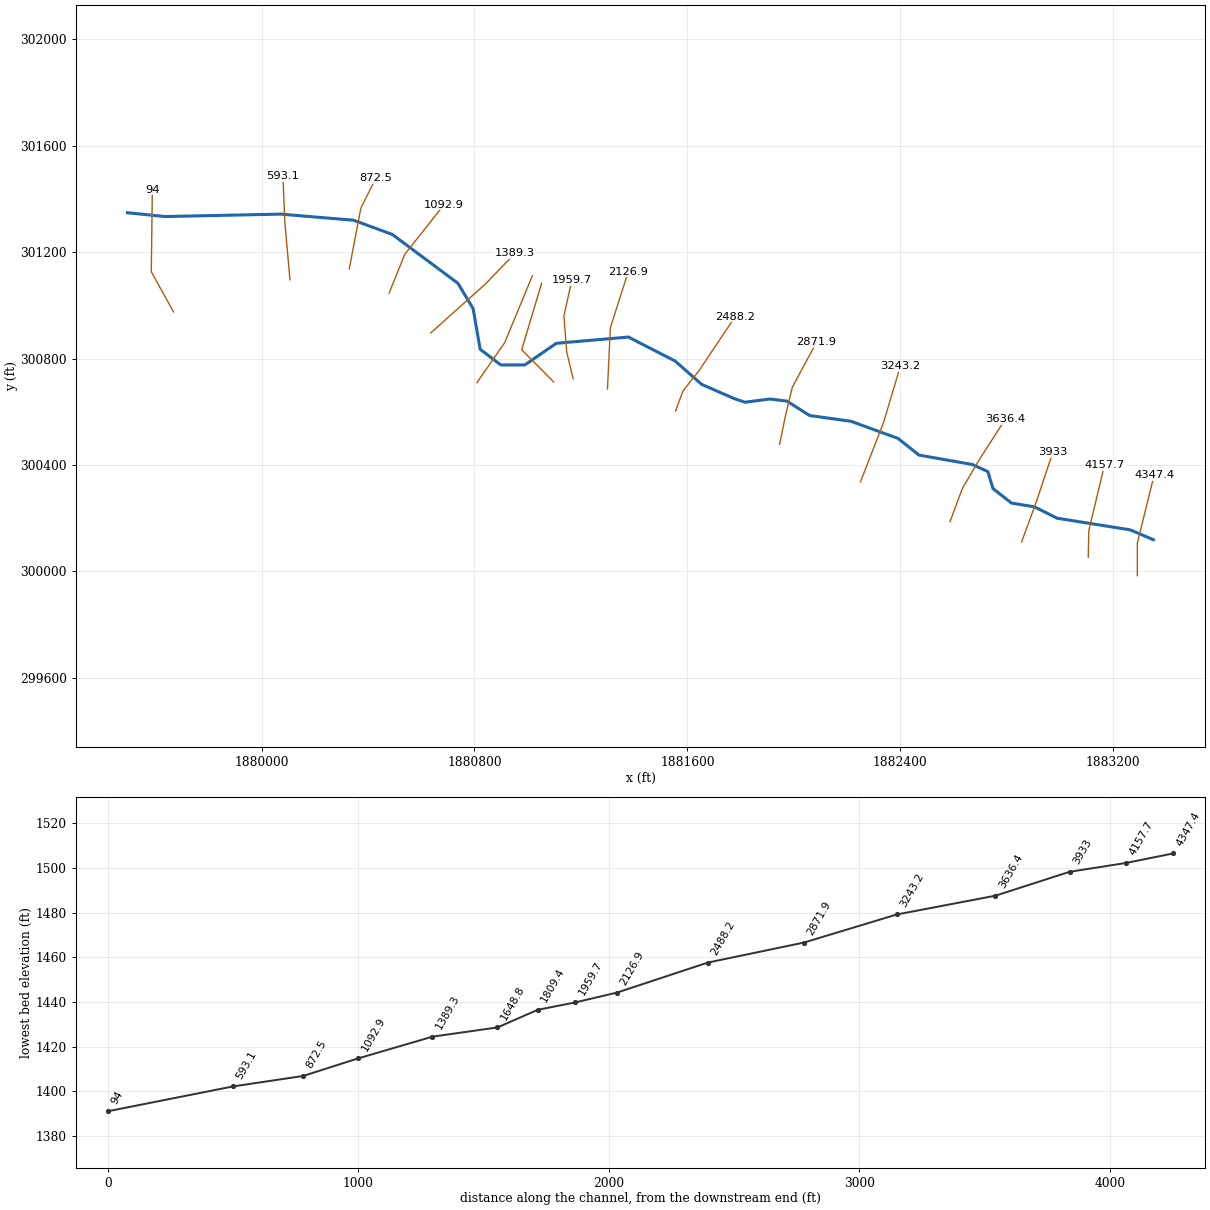
--- TIBBSRN.prj (project) ---

Proj Title=TIBBSRN
Current Plan=p01
Default Exp/Contr=0,0
English Units
Geom File=g01
Flow File=f01
Plan File=p01
BEGIN DESCRIPTION:
END DESCRIPTION:
DSS Export Rating Curves= 0
DSS Export Rating Curve Sorted= 0
DSS Export Volume Flow Curves= 0
DXF OffsetX= 0
DXF OffsetY= 0
DXF ScaleX= 0
DXF ScaleY= 0

--- TIBBSRN.p01 (plan) ---

Plan Title=Floodplain
Program Version=4.00
Geom File=g01
Flow File=f01
K Sum by GR=0
Std Step Tol=0.01
Critical Tol=0.01
Num of Std Step Trials=20
Max Error Tol=0.3
Flow Tol Ratio=0.001
Split Flow NTrial=30
Split Flow Tol=0.02
Split Flow Ratio=0.02
Log Output Level=0
Friction Slope Method=1
Unsteady Friction Slope Method=2
Unsteady Bridges Friction Slope Method=1
Global Log Level=0
CheckData=False
Run HTab=0
Run UNet=0
Run PostProcess=0
UNET Theta=0
UNET Theta Warmup=0
UNET ZTol=0
UNET ZSATol=0
UNET MxIter=0
UNET MaxInSteps=0
UNET DtIC=0
UNET DtMin=0
UNET MaxCRTS=0
UNET WFStab=0
UNET SFStab=0
UNET WFX=0
UNET SFX=0
UNET DSS MLevel=0
UNET DZMax Abort=0
UNET Convert EG Bridges=0
UNET Use Existing IB Tables=0
UNET Froude Limit=0
UNET Froude Power=0
Write IC File=0
Echo Input=False
Echo Output=False
Write Detailed=0

--- TIBBSRN.f01 (steady flow) ---

Flow Title=NFF Regression Equation
Program Version=4.00
Number of Profiles=1
Profile Names=P100yr
River Rch & RM=TIBBSRN,Main      ,4347.4
521.0477
River Rch & RM=TIBBSRN,Main      ,94
578.8516
Boundary for River Rch & Prof#=TIBBSRN,Main      ,1
Up Type=0
Dn Type=3
Dn Slope=0.024948

--- TIBBSRN.g01 (geometry) ---

Geom Title=USGS 10m DEM
Program Version=4.10

River Reach=TIBBSRN         ,Main
Reach XY= 30
     1883350.779      300119.376     1883263.663      300156.377
      1882989.52      300200.105      1882903.33      300243.002
     1882817.609      300257.108     1882748.114      300311.638
     1882728.887      300375.232     1882671.209      300401.852
     1882470.074      300437.347      1882391.69      300499.906
     1882214.958      300564.239     1882059.236      300586.065
     1881973.515      300640.318     1881909.496      300647.913
     1881815.963      300635.978     1881774.731      300650.084
     1881653.203      300703.252       1881554.3      300790.471
     1881378.288       300880.86     1881107.413      300857.332
      1880989.14      300775.952      1880899.08      300775.952
     1880821.413      300834.865     1880794.913       300987.54
     1880737.621      301083.026     1880491.311      301266.403
     1880345.584      301319.827      1880072.72      301342.751
     1879637.144      301333.677     1879495.868         301348.

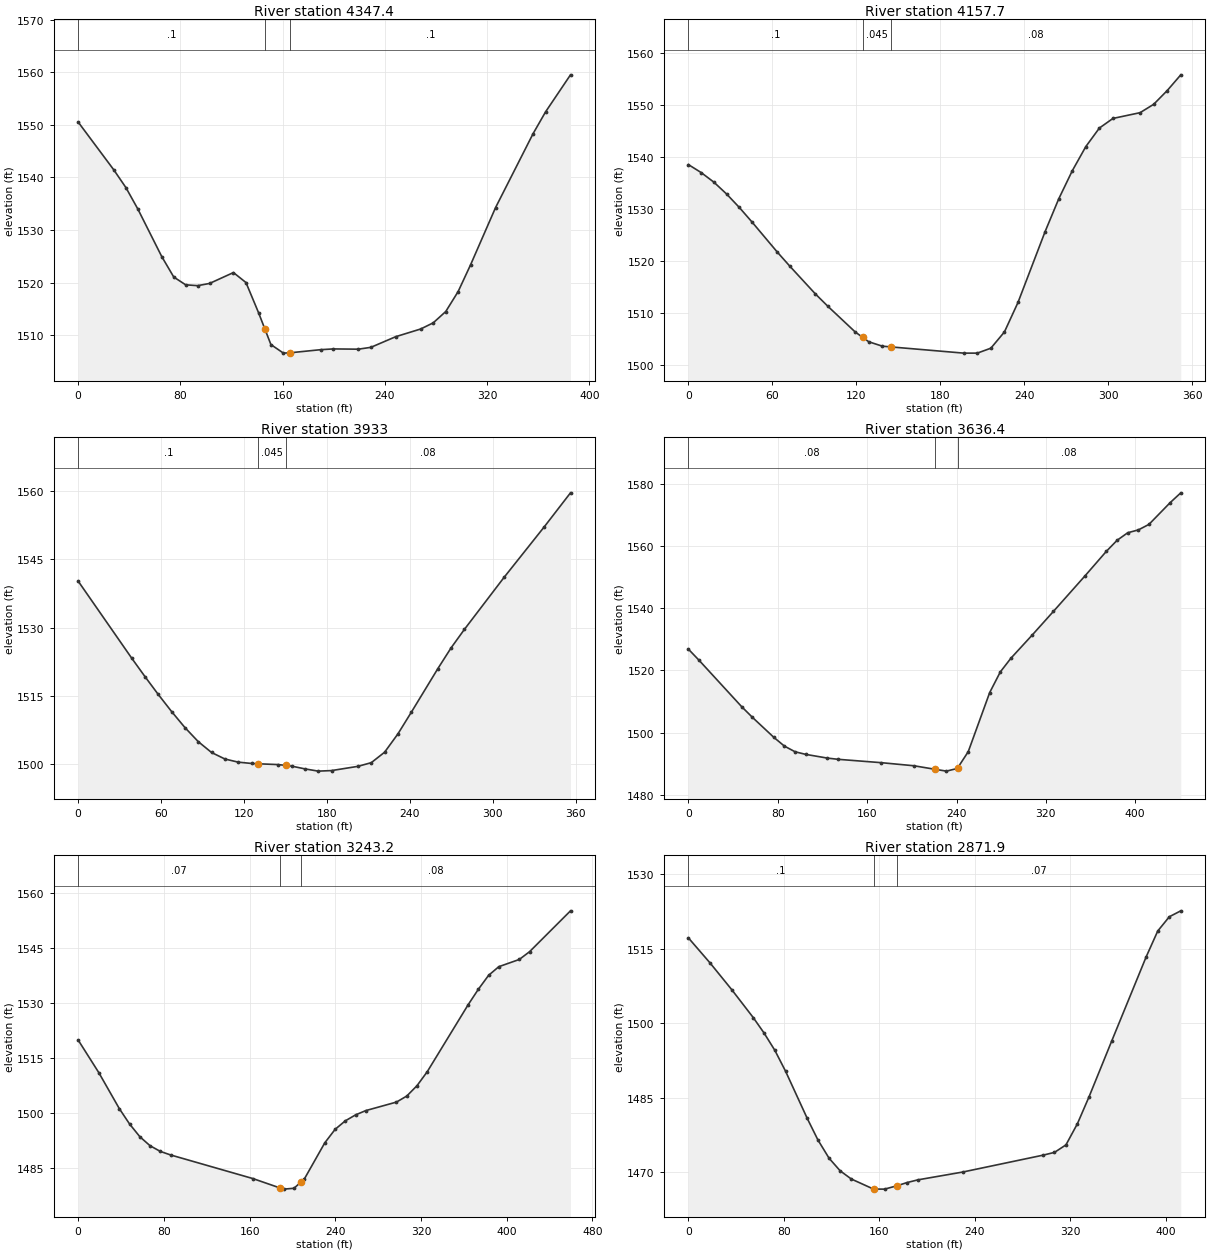
Type RM Length L Ch R = 1 ,4347.4  ,189.6,189.7,189.8
XS GIS Cut Line= 3
     1883290.519      299984.394     1883290.519      300105.921
     1883353.453      300361.998
#Sta/Elev= 30
       0 1550.51      28 1541.38    37.4 1538.03    46.7 1533.97    65.4 1524.93
    74.8 1521.04    84.1 1519.56    93.5  1519.4   102.8 1519.82   121.5 1521.89
   131.3 1519.99   141.1 1514.28     146 1511.21   150.8  1508.2   160.6 1506.57
     166 1506.64   189.9 1507.23   199.7 1507.37   219.2 1507.32     229 1507.67
   248.5  1509.7     268 1511.16   277.8 1512.33   287.6 1514.48   297.3 1518.28
   307.1 1523.41   326.6 1534.26   355.9 1548.29   365.7 1552.45   385.2 1559.49
#Mann= 3 , 0 , 0
       0      .1       0     146    .045       0     166      .1       0
Bank Sta=146,166
XS Rating Curve= 0 ,0
Exp/Cntr=0.3,0.1

Type RM Length L Ch R = 1 ,4157.7  ,227.4,224.8,222
XS GIS Cut Line= 3
     1883106.057      300053.838     1883108.227      300153.664
     1883166.821       300398.89
#Sta/Elev= 30
       0 1538.59     9.1 1537.06    18.2 1535.21    27.2 1532.95    36.3 1530.36
    45.4 1527.55    63.5 1521.75    72.6 1518.99    90.8 1513.67    99.8 1511.27
   119.2 1506.36   124.6 1505.31   128.9 1504.47   138.6 1503.62   144.6 1503.48
   196.8 1502.28   206.5 1502.28   216.2 1503.23   225.9 1506.36   235.6 1512.04
     255  1525.7   264.7 1531.98   274.4  1537.4   284.1 1542.07   293.8 1545.64
   303.5 1547.49   322.9  1548.6   332.6 1550.21   342.3 1552.86     352 1555.89
#Mann= 3 , 0 , 0
       0      .1       0   124.6    .045       0   144.6     .08       0
Bank Sta=124.6,144.6
XS Rating Curve= 0 ,0
Exp/Cntr=0.3,0.1

Type RM Length L Ch R = 1 ,3933    ,300.4,296.6,292.6
XS GIS Cut Line= 3
     1882855.677      300110.804     1882912.101      300264.884
     1882972.864      300447.176
#Sta/Elev= 29
       0 1540.23    38.6  1523.3    48.3 1519.19    57.9 1515.26    67.6 1511.47
    77.2 1507.95    86.9 1504.83    96.5 1502.44   106.2    1501   115.8 1500.31
   125.5 1500.02   130.4 1499.95   144.8 1499.77   150.4 1499.58   154.4 1499.44
   164.1 1498.82   173.7 1498.33   183.3 1498.45   202.5 1499.39   212.1  1500.2
   221.7  1502.5   231.3 1506.52     241  1511.3   260.2 1520.92   269.8 1525.51
   279.4 1529.57   308.2 1541.08     337 1552.12   356.2  1559.7
#Mann= 3 , 0 , 0
       0      .1       0   130.4    .045       0   150.4     .08       0
Bank Sta=130.4,150.4
XS Rating Curve= 0 ,0
Exp/Cntr=0.3,0.1

Type RM Length L Ch R = 1 ,3636.4  ,388.8,393.1,396.8
XS GIS Cut Line= 4
      1882586.58      300186.759     1882633.147      300312.043
     1882697.257      300421.134     1882794.913      300573.044
#Sta/Elev= 30
       0 1526.83     9.6 1523.23    47.7 1508.32    57.3  1504.9    76.4 1498.49
    85.9 1495.66    95.5 1493.83     105    1493   124.1 1491.82   133.7 1491.42
   172.6 1490.33   201.8 1489.34   221.1 1488.18     231 1487.61   240.7 1488.47
   241.1 1488.69   250.5 1493.87   269.7 1512.88   279.2 1519.52   288.7 1523.93
   307.7 1531.36   326.7 1538.97   355.2 1550.49   374.2 1558.34   383.8 1561.88
   393.3  1564.3   402.8 1565.21   412.3 1566.99   431.3 1573.99   440.8 1577.14
#Mann= 3 , 0 , 0
       0     .08       0   221.1    .045       0   241.1     .08       0
Bank Sta=221.1,241.1
XS Rating Curve= 0 ,0
Exp/Cntr=0.3,0.1

Type RM Length L Ch R = 1 ,3243.2  ,367.3,371.4,374.2
XS GIS Cut Line= 3
     1882250.208      300336.499     1882337.014      300560.023
     1882399.948      300770.526
#Sta/Elev= 30
       0 1519.91    19.2 1511.04    38.4 1501.19      48 1496.98    57.6  1493.5
    67.1 1491.05    76.7  1489.5    86.3 1488.53   163.1 1482.08   188.1 1479.55
   191.8  1479.2   201.4 1479.43   208.1 1481.17     211 1481.92   230.2 1491.85
   239.8 1495.52   249.3 1497.84   258.9 1499.47   268.4 1500.64   297.1 1502.97
   306.7 1504.62   316.2 1507.43   325.8 1511.26     364 1529.56   373.5 1533.77
   383.1 1537.59   392.6 1539.94   411.7 1541.91   421.3 1544.03   459.5 1555.19
#Mann= 3 , 0 , 0
       0     .07       0   188.1    .045       0   208.1     .08       0
Bank Sta=188.1,208.1
XS Rating Curve= 0 ,0
Exp/Cntr=0.3,0.1

Type RM Length L Ch R = 1 ,2871.9  ,394.3,383.7,372.5
XS GIS Cut Line= 4
     1881946.389      300477.558      1881968.09      300583.894
     1881994.132      300692.401     1882085.278      300861.672
#Sta/Elev= 28
       0  1517.2    18.1 1512.16    36.2  1506.8    54.3 1501.15    63.3 1498.06
    72.4 1494.55    81.4 1490.33    99.5 1480.85   108.5 1476.49   117.8 1472.83
   127.1 1470.29   136.4 1468.65     155 1466.62   164.3 1466.61     175 1467.31
   182.9 1467.92   192.2 1468.48   229.7 1470.05     297 1473.45   306.6 1474.01
   316.2 1475.52   325.8 1479.78   335.5 1485.18   354.7 1496.54   383.5 1513.45
   393.1  1518.6   402.8 1521.47   412.4 1522.66
#Mann= 3 , 0 , 0
       0      .1       0     155    .045       0     175     .07       0
Bank Sta=155,175
XS Rating Curve= 0 ,0
Exp/Cntr=0.3,0.1

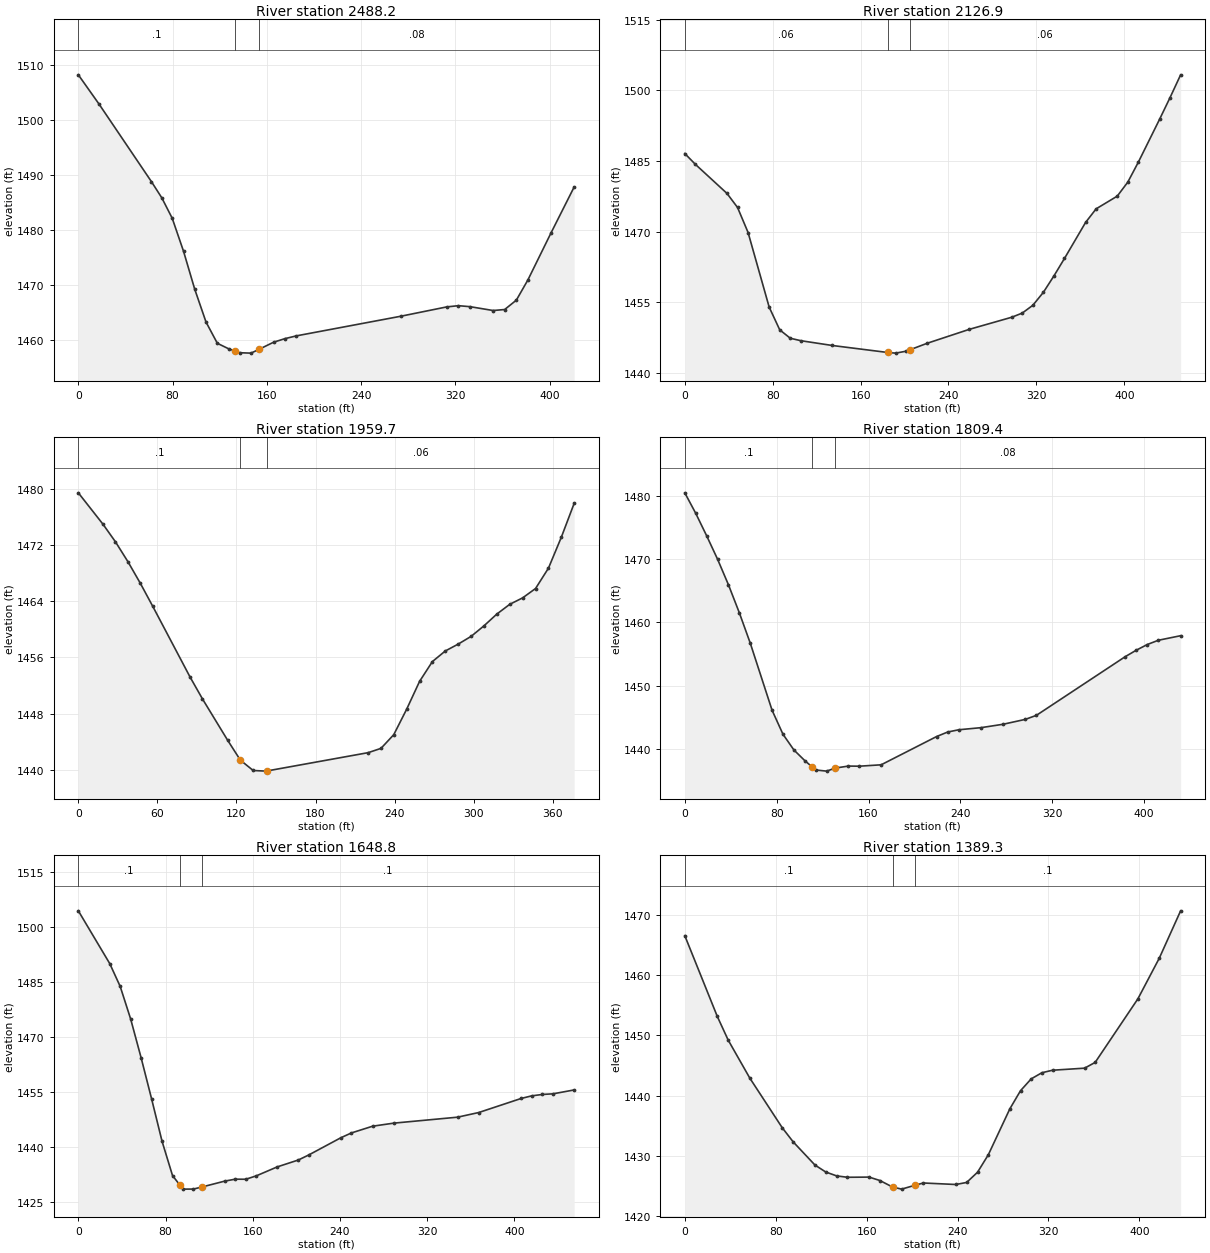
Type RM Length L Ch R = 1 ,2488.2  ,345.4,361.3,376.7
XS GIS Cut Line= 4
     1881555.764      300603.426     1881583.167        300678.3
     1881642.569      300753.165     1881779.288      300957.158
#Sta/Elev= 27
       0 1508.26    17.7  1502.9      62 1488.85    70.9 1485.87    79.7 1482.17
    89.3 1476.17    98.8 1469.27   108.4 1463.29     118 1459.43   127.5 1458.44
   133.2 1458.01   137.1 1457.71   146.6 1457.64   153.2 1458.31   165.7 1459.62
   175.3 1460.27   185.1 1460.78   273.5 1464.34   312.8 1466.05   322.6 1466.27
   332.5 1466.09   352.1 1465.39   361.9 1465.57   371.8 1467.27   381.6 1470.94
   401.2 1479.48   420.9 1487.86
#Mann= 3 , 0 , 0
       0      .1       0   133.2    .045       0   153.2     .08       0
Bank Sta=133.2,153.2
XS Rating Curve= 0 ,0
Exp/Cntr=0.3,0.1

Type RM Length L Ch R = 1 ,2126.9  ,164.1,167.3,170.3
XS GIS Cut Line= 3
     1881299.687      300685.891     1881310.538      300915.926
     1881377.812      301126.429
#Sta/Elev= 30
       0 1486.61     9.6 1484.32    38.4 1478.14      48 1475.16    57.6 1469.84
    76.8    1454    86.4 1449.18      96 1447.39   105.6 1446.87   134.3 1445.85
   184.6 1444.37   191.9 1444.23   201.5 1444.64   204.6 1444.91   220.7 1446.33
   259.1 1449.29   297.6 1451.85   307.2 1452.74   316.8 1454.39   326.4 1457.15
     336 1460.63   345.6 1464.34   364.8 1471.98   374.4 1474.87   393.6 1477.56
   403.2 1480.53   412.8 1484.77   432.1 1493.86   441.7  1498.5   451.3 1503.32
#Mann= 3 , 0 , 0
       0     .06       0   184.6    .045       0   204.6     .06       0
Bank Sta=184.6,204.6
XS Rating Curve= 0 ,0
Exp/Cntr=0.3,0.1

Type RM Length L Ch R = 1 ,1959.7  ,132.4,150.3,167.9
XS GIS Cut Line= 4
      1881170.77      300724.353     1881146.465      300825.047
     1881136.048      300960.464     1881165.562      301094.145
#Sta/Elev= 30
       0 1479.41    18.8 1474.92    28.2 1472.43    37.7 1469.59    47.1 1466.52
    56.5 1463.25    84.8 1453.19    94.2 1450.08   113.3  1444.2     123 1441.36
   132.7 1439.89   142.4  1439.8     143 1439.82     220 1442.43   229.7 1443.04
   239.4 1444.99   249.2 1448.62     259 1452.58   268.7 1455.39   278.5  1456.9
   288.3 1457.88   298.1 1458.98   307.8 1460.47   317.6 1462.15   327.4 1463.54
   337.2 1464.46     347 1465.79   356.8 1468.69   366.5 1473.06   376.3 1477.91
#Mann= 3 , 0 , 0
       0      .1       0     123    .045       0     143     .06       0
Bank Sta=123,143
XS Rating Curve= 0 ,0
Exp/Cntr=0.3,0.1

Type RM Length L Ch R = 1 ,1809.4  ,195.4,160.6,125.3
XS GIS Cut Line= 3
     1881097.864      300711.933     1880977.367      300833.207
     1881052.292      301083.026
#Sta/Elev= 30
       0 1480.47     9.5 1477.24      19 1473.69    28.5 1469.99      38 1465.94
    47.5  1461.5      57 1456.71      76  1446.1    85.5  1442.3      95 1439.82
   104.5 1438.13   111.2 1437.09     114 1436.65   123.5 1436.47   131.2 1436.96
   142.5 1437.27     152 1437.25     171 1437.47   219.3 1441.94   228.9 1442.65
   238.6 1443.01   257.9 1443.34   277.2 1443.88   296.5 1444.65   306.2 1445.29
   383.5 1454.56   393.1 1455.58   402.8 1456.49   412.4 1457.16   431.8 1457.88
#Mann= 3 , 0 , 0
       0      .1       0   111.2    .045       0   131.2     .08       0
Bank Sta=111.2,131.2
XS Rating Curve= 0 ,0
Exp/Cntr=0.3,0.1

Type RM Length L Ch R = 1 ,1648.8  ,265.4,259.5,253.5
XS GIS Cut Line= 3
     1880809.236      300709.762     1880913.403      300859.502
     1881017.569      301111.238
#Sta/Elev= 30
       0 1504.36    28.8    1490    38.4 1483.77      48  1474.9    57.6 1464.34
    67.2 1453.16    76.8  1441.6    86.4 1432.27    93.2 1429.66      96 1428.58
   105.6  1428.6   113.2 1429.15   134.4 1430.77     144 1431.29   153.6 1431.27
   163.2 1432.19   182.4 1434.63   201.9 1436.52   211.6 1437.92   240.8 1442.57
   250.5 1443.88     270 1445.72   289.4 1446.55   347.8 1448.17   367.3 1449.44
   406.2 1453.27   415.9 1453.98   425.6 1454.36   435.4 1454.53   454.8 1455.59
#Mann= 3 , 0 , 0
       0      .1       0    93.2    .045       0   113.2      .1       0
Bank Sta=93.2,113.2
XS Rating Curve= 0 ,0
Exp/Cntr=0.3,0.1

Type RM Length L Ch R = 1 ,1389.3  ,291.4,296.4,300.8
XS GIS Cut Line= 3
     1880635.625      300896.394     1880841.788      301080.856
     1880952.465      301195.874
#Sta/Elev= 30
       0 1466.59    28.6 1453.16    38.2 1449.22    57.2 1442.91    85.8 1434.64
    95.4  1432.3   114.5 1428.46     124  1427.3   133.6 1426.65   143.1 1426.42
   162.2 1426.45   171.7 1425.88   182.8  1424.8   190.8 1424.45   202.8 1425.11
   209.9 1425.47   238.5 1425.22     248 1425.56   257.6 1427.26   267.1 1430.17
     286 1437.79   295.4 1440.81   304.8 1442.78   314.2  1443.8   323.6 1444.22
   351.8 1444.56   361.1 1445.52   398.7 1456.09   417.5 1462.84   436.3 1470.72
#Mann= 3 , 0 , 0
       0      .1       0   182.8    .045       0   202.8      .1       0
Bank Sta=182.8,202.8
XS Rating Curve= 0 ,0
Exp/Cntr=0.3,0.1

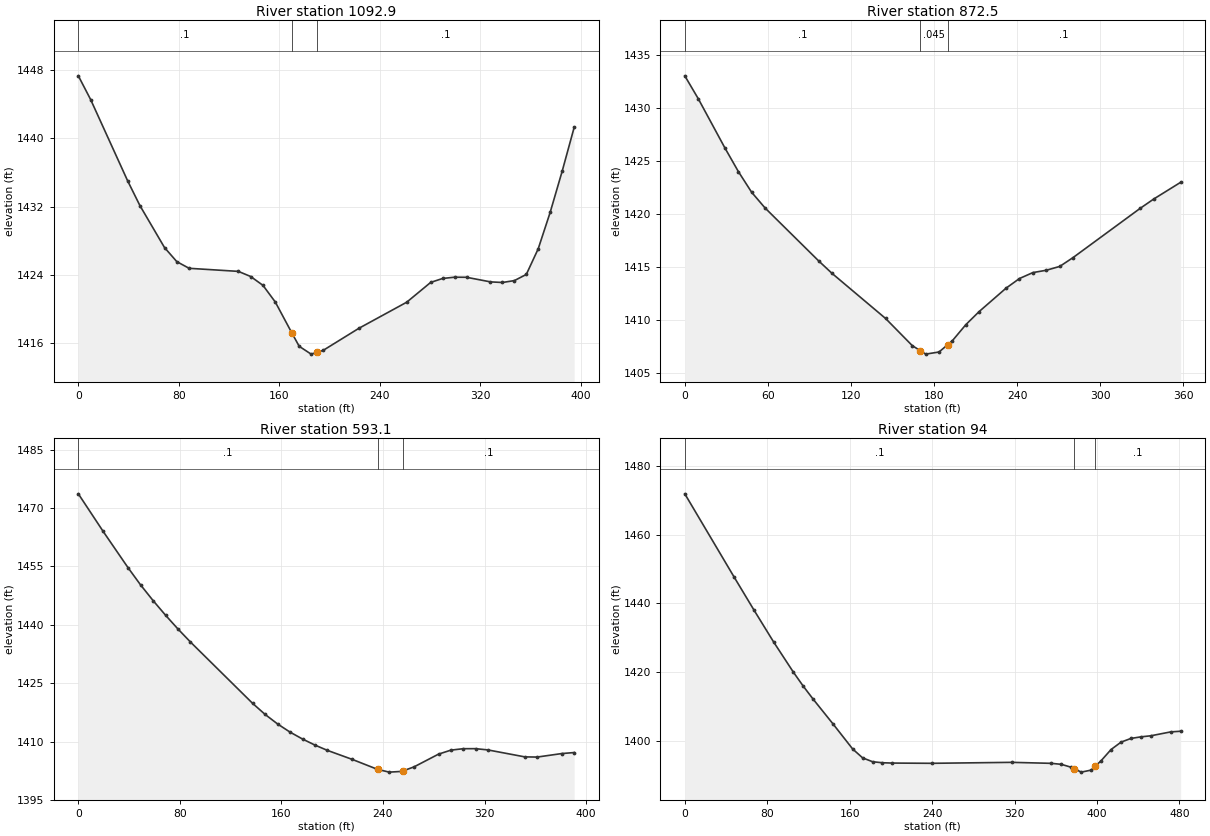
Type RM Length L Ch R = 1 ,1092.9  ,208.7,220.4,232.3
XS GIS Cut Line= 3
     1880479.375      301046.134     1880537.969      301191.533
     1880685.538      301378.165
#Sta/Elev= 30
       0 1447.31     9.8 1444.53    39.2 1435.03      49 1432.12    68.6  1427.2
    78.4 1425.55    88.2 1424.77   127.4 1424.41   137.2 1423.81     147 1422.77
   156.8 1420.82   169.9 1417.22   175.8 1415.64   185.3 1414.72   189.9 1414.93
   194.8 1415.15   223.4 1417.75   261.4  1420.8   280.5 1423.12     290 1423.58
   299.5 1423.73     309 1423.72   328.1 1423.18   337.6 1423.11   347.1 1423.33
   356.6 1424.05   366.1 1427.06   375.6 1431.32   385.2 1436.16   394.7 1441.27
#Mann= 3 , 0 , 0
       0      .1       0   169.9    .045       0   189.9      .1       0
Bank Sta=169.9,189.9
XS Rating Curve= 0 ,0
Exp/Cntr=0.3,0.1

Type RM Length L Ch R = 1 ,872.5   ,273.5,279.4,285
XS GIS Cut Line= 3
     1880329.635       301137.28     1880373.038      301365.144
     1880429.462      301477.992
#Sta/Elev= 26
       0 1433.03     9.7 1430.88      29 1426.23    38.7 1424.01    48.3 1422.06
      58 1420.58    96.6 1415.61   106.3 1414.43     145 1410.18   164.3 1407.62
   169.9 1407.16     174 1406.82   183.6 1407.02   189.9 1407.71   193.3 1408.09
     203  1409.6   212.6 1410.83     232 1413.03   241.7 1413.94   251.4  1414.5
   261.1 1414.72   270.8 1415.08   280.5 1415.92     329 1420.56   338.7 1421.43
   358.1    1423
#Mann= 3 , 0 , 0
       0      .1       0   169.9    .045       0   189.9      .1       0
Bank Sta=169.9,189.9
XS Rating Curve= 0 ,0
Exp/Cntr=0.3,0.1

Type RM Length L Ch R = 1 ,593.1   ,500.5,499.1,497.7
XS GIS Cut Line= 3
     1880106.749      301096.148     1880087.559      301311.098
     1880080.299      301485.703
#Sta/Elev= 30
       0 1473.67    19.6 1463.99    39.2 1454.67      49 1450.28    58.9 1446.23
    68.7 1442.48    78.5 1438.93    88.3  1435.6   137.3 1419.82   147.1 1416.99
     157 1414.52   166.8 1412.43   176.6 1410.66   186.4  1409.1   196.2 1407.74
   215.8 1405.42   235.8 1402.85   244.9 1402.15   254.6 1402.33   255.8 1402.47
   264.4 1403.49   283.8 1406.78   293.5  1407.8   303.2 1408.17   312.9 1408.18
   322.6 1407.86   351.7 1406.07   361.4 1406.02   380.8 1406.92   390.6 1407.18
#Mann= 3 , 0 , 0
       0      .1       0   235.8    .045       0   255.8      .1       0
Bank Sta=235.8,255.8
XS Rating Curve= 0 ,0
Exp/Cntr=0.3,0.1

Type RM Length L Ch R = 1 ,94      ,90,94,97.6
XS GIS Cut Line= 3
     1879669.045      300975.387     1879585.712      301126.429
     1879589.618      301435.023
#Sta/Elev= 30
       0 1471.82    47.9 1447.64    67.1 1438.09    86.2 1428.81   105.4 1420.03
     115 1415.96   124.6 1412.19   143.8 1405.03   162.9 1397.74   172.5 1395.18
   182.2 1394.05   191.8 1393.75   201.4 1393.66     240 1393.59   317.2 1393.87
   355.8 1393.58   365.4 1393.29     375 1392.44     378    1392   384.7 1391.03
   394.3 1391.62     398 1392.67     404 1394.36   413.6 1397.59   423.3 1399.74
   432.9 1400.81   442.6 1401.27   452.2 1401.58   471.5 1402.71   481.1  1402.9
#Mann= 3 , 0 , 0
       0      .1       0     378    .045       0     398      .1       0
Bank Sta=378,398
XS Rating Curve= 0 ,0
Exp/Cntr=0.3,0.1

Chan Stop Cuts=-1
Use User Specified Reach Order=0
Composite Channel Slope=5